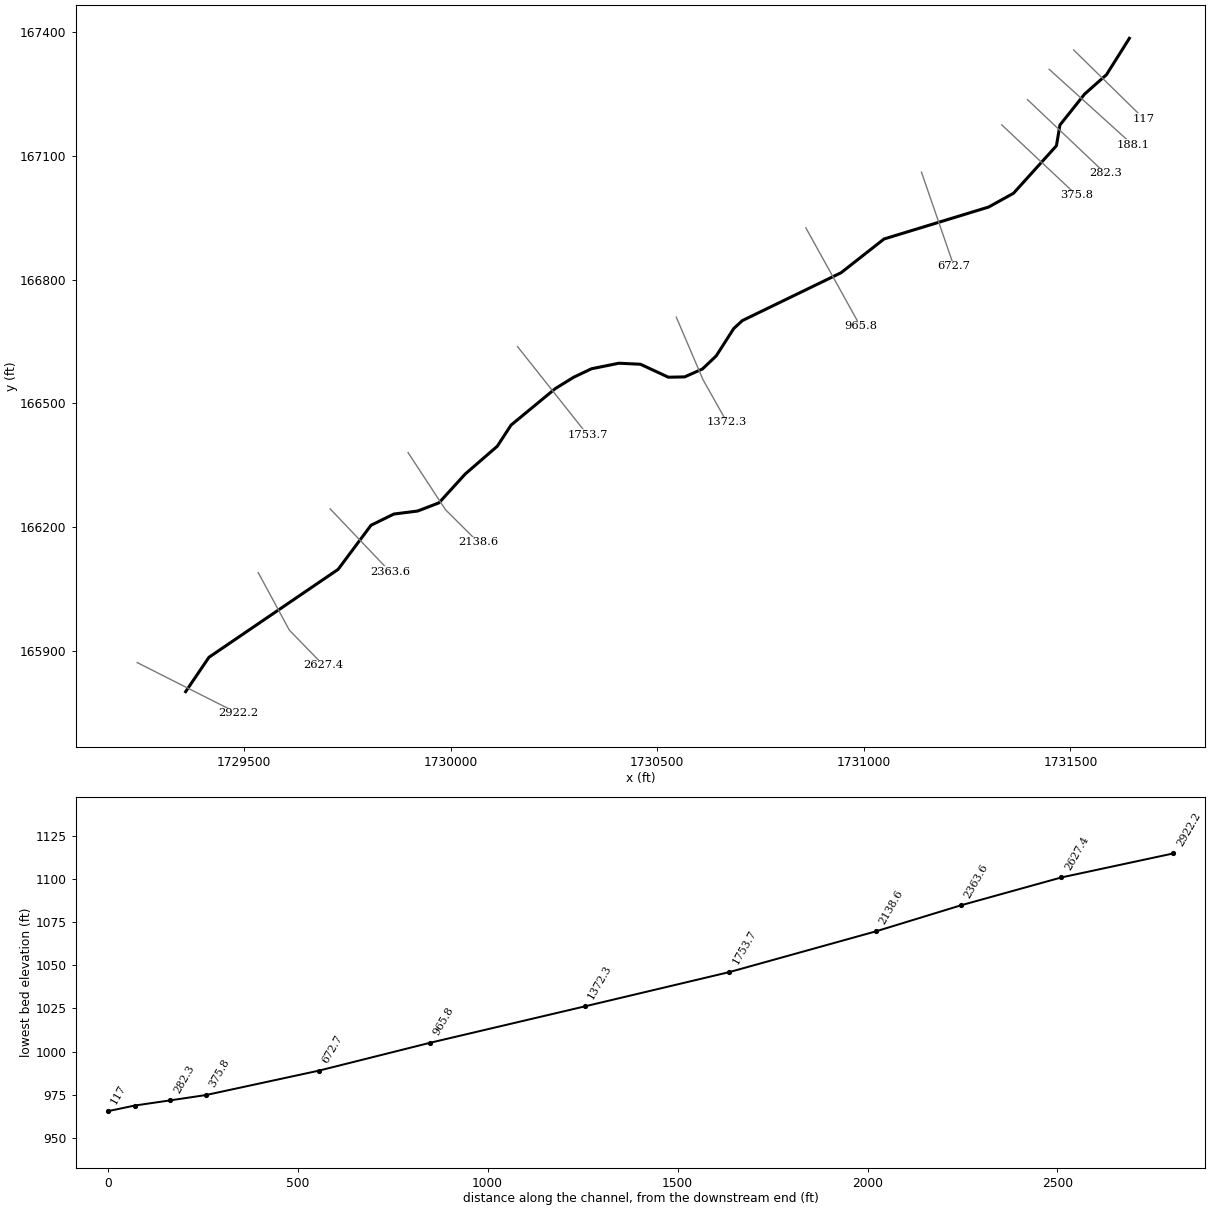
--- Coon Branch.prj (project) ---

Proj Title=Coon Branch
Current Plan=p01
Default Exp/Contr=0,0
English Units
Geom File=g01
Flow File=f01
Plan File=p01
BEGIN DESCRIPTION:
END DESCRIPTION:
DSS Export Rating Curves= 0
DSS Export Rating Curve Sorted= 0
DSS Export Volume Flow Curves= 0
DXF OffsetX= 0
DXF OffsetY= 0
DXF ScaleX= 0
DXF ScaleY= 0

--- Coon Branch.p01 (plan) ---

Plan Title=Floodplain
Program Version=4.00
Geom File=g01
Flow File=f01
K Sum by GR=0
Std Step Tol=0.01
Critical Tol=0.01
Num of Std Step Trials=20
Max Error Tol=0.3
Flow Tol Ratio=0.001
Split Flow NTrial=30
Split Flow Tol=0.02
Split Flow Ratio=0.02
Log Output Level=0
Friction Slope Method=1
Unsteady Friction Slope Method=2
Unsteady Bridges Friction Slope Method=1
Global Log Level=0
CheckData=False
Run HTab=0
Run UNet=0
Run PostProcess=0
UNET Theta=0
UNET Theta Warmup=0
UNET ZTol=0
UNET ZSATol=0
UNET MxIter=0
UNET MaxInSteps=0
UNET DtIC=0
UNET DtMin=0
UNET MaxCRTS=0
UNET WFStab=0
UNET SFStab=0
UNET WFX=0
UNET SFX=0
UNET DSS MLevel=0
UNET DZMax Abort=0
UNET Convert EG Bridges=0
UNET Use Existing IB Tables=0
UNET Froude Limit=0
UNET Froude Power=0
Write IC File=0
Echo Input=False
Echo Output=False
Write Detailed=0

--- Coon Branch.f01 (steady flow) ---

Flow Title=NFF Regression Equation
Program Version=4.00
Number of Profiles=1
Profile Names=P100yr
River Rch & RM=Coon Branch,Main      ,2922.2
544.3917
River Rch & RM=Coon Branch,Main      ,2363.6
588.8498
River Rch & RM=Coon Branch,Main      ,282.3
646.0726
Boundary for River Rch & Prof#=Coon Branch,Main      ,1
Up Type=0
Dn Type=3
Dn Slope=0.027787

--- Coon Branch.g01 (geometry) ---

Geom Title=Geometry
Program Version=4.00

River Reach=Coon Branch     ,Main
Reach XY= 30
     1729358.481      165801.128     1729414.804      165884.395
     1729727.509      166097.655     1729807.083      166204.645
      1729862.53      166231.905     1729919.995      166239.131
     1729971.662      166259.035     1730035.108      166328.931
     1730112.752      166396.337     1730146.028      166447.532
     1730252.936      166535.971     1730297.685      166563.672
     1730340.723      166584.167     1730407.245      166597.621
     1730459.167      166595.142     1730526.836      166563.672
     1730566.185      166564.444     1730609.392      166583.733
     1730642.569      166615.366     1730685.004       166681.72
     1730705.836      166701.009     1730944.658      166816.983
     1731048.753      166898.894     1731301.875      166976.343
     1731362.114      167009.808     1731465.986      167125.002
     1731474.519      167175.343     1731534.245      167250.428
     1731587.146      167297.356     1731642.531      167385.512

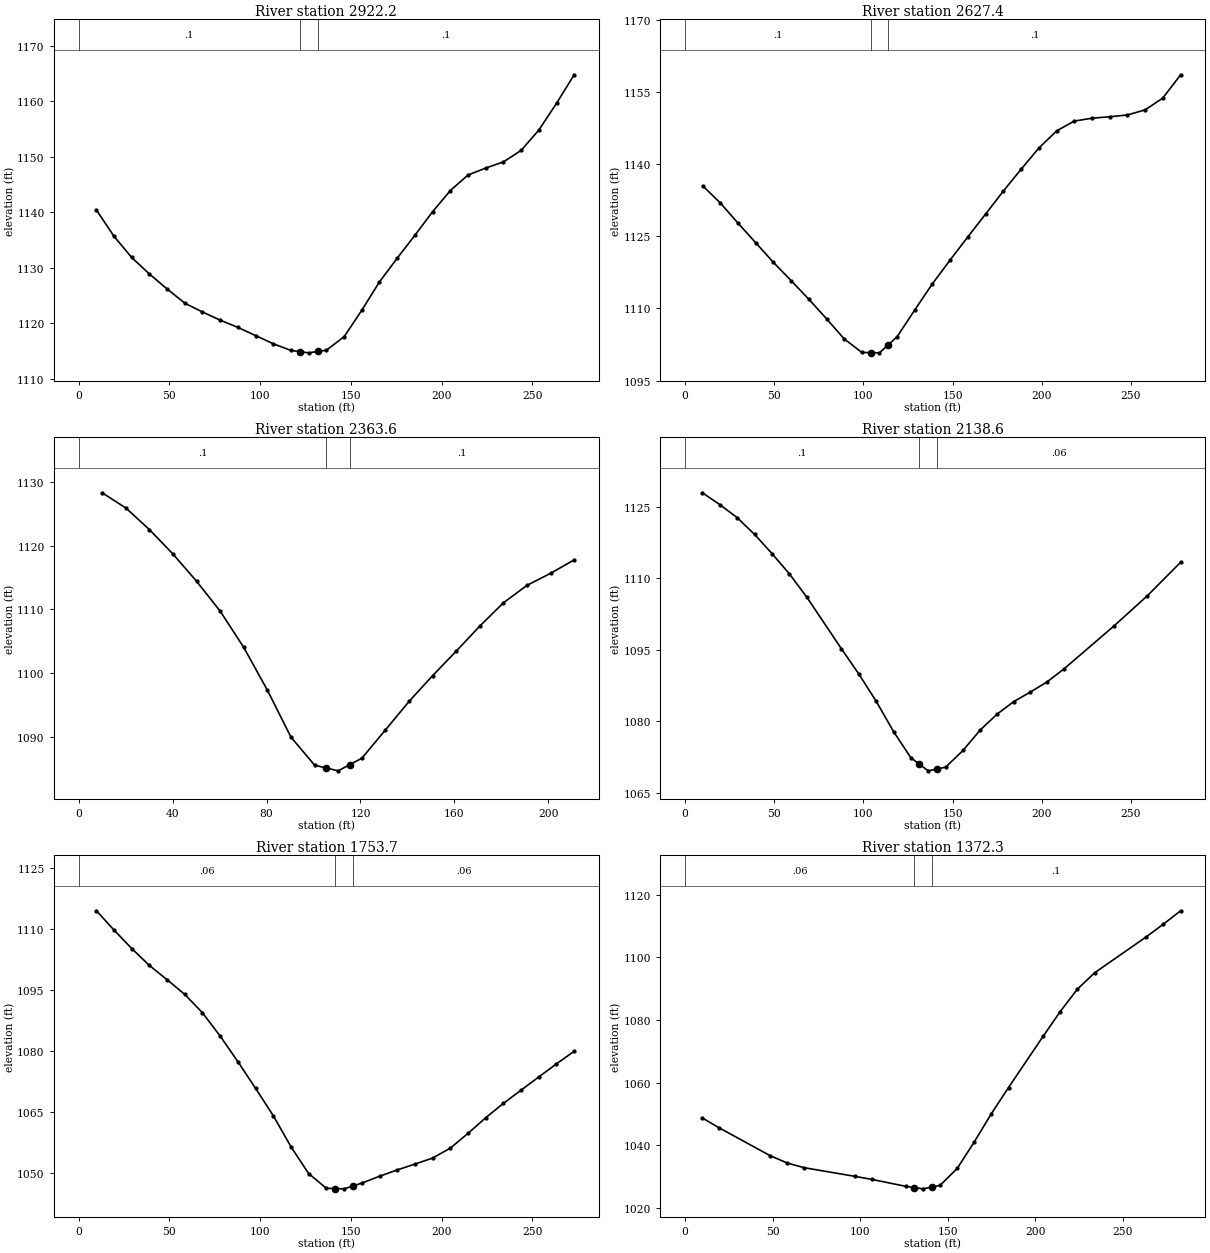
Type RM Length L Ch R = 1 ,2922.2  ,307,294.8,282.6
XS GIS Cut Line= 3
     1729241.187      165871.656     1729362.994      165810.052
     1729484.802      165748.447
#Sta/Elev= 30
     9.8 1140.39    19.5 1135.65    29.2 1131.85      39 1128.86    48.8 1126.15
    58.5  1123.6    68.2 1122.02      78 1120.54    87.7 1119.24    97.5 1117.76
   107.3 1116.28     117 1115.08   121.8 1114.87   126.7 1114.65   131.8  1114.9
   136.5 1115.12   146.3 1117.57     156 1122.33   165.7 1127.42   175.5 1131.71
   185.3 1135.86     195 1140.08   204.8 1143.91   214.5  1146.7   224.3 1147.96
     234 1149.06   243.8 1151.15   253.5 1154.79   263.3 1159.64     273 1164.77
#Mann= 3 , 0 , 0
       0      .1       0   121.8    .045       0   131.8      .1       0
Bank Sta=121.8,131.8
XS Rating Curve= 0 ,0
Exp/Cntr=0.3,0.1

Type RM Length L Ch R = 1 ,2627.4  ,261,263.8,269.2
XS GIS Cut Line= 3
     1729534.118      166089.898       1729609.4      165950.371
     1729692.482      165864.708
#Sta/Elev= 30
     9.9 1135.48    19.8 1131.91    29.7 1127.71    39.6 1123.66    49.5 1119.58
    59.5 1115.76    69.4  1111.9    79.3 1107.85    89.2 1103.67    99.1 1100.84
     104  1100.8     109 1100.76     114 1102.45   118.9 1104.11   128.8 1109.68
   138.7 1115.13   148.6 1120.05   158.5 1124.84   168.5 1129.61   178.4 1134.36
   188.4 1138.92   198.3 1143.31   208.3  1146.9   218.2 1148.95   228.2 1149.55
   238.1 1149.85     248 1150.22     258 1151.28   267.9 1153.74   277.9 1158.58
#Mann= 3 , 0 , 0
       0      .1       0     104    .045       0     114      .1       0
Bank Sta=104,114
XS Rating Curve= 0 ,0
Exp/Cntr=0.3,0.1

Type RM Length L Ch R = 1 ,2363.6  ,228.6,224.9,221.2
XS GIS Cut Line= 2
     1729708.143      166244.476     1729853.602      166091.584
#Sta/Elev= 23
      10 1128.29    20.1 1125.91    30.1 1122.53    40.2 1118.67    50.2 1114.42
    60.3 1109.71    70.3 1104.04    80.4 1097.31    90.4 1089.97   100.5 1085.56
   105.5 1085.12   110.5 1084.68   115.5 1085.66   120.6 1086.66   130.6 1091.08
   140.7 1095.57   150.7  1099.6   160.8 1103.46   170.8 1107.38   180.9 1111.04
   190.9 1113.77     201 1115.67     211 1117.77
#Mann= 3 , 0 , 0
       0      .1       0   105.5    .045       0   115.5      .1       0
Bank Sta=105.5,115.5
XS Rating Curve= 0 ,0
Exp/Cntr=0.3,0.1

Type RM Length L Ch R = 1 ,2138.6  ,383,385,386.9
XS GIS Cut Line= 3
     1729896.754      166380.881     1729987.383      166242.352
     1730066.889      166163.156
#Sta/Elev= 26
     9.7 1127.97    19.5 1125.48    29.2 1122.74      39 1119.21    48.7  1115.2
    58.4 1110.97    68.2 1106.06    87.6 1095.22    97.4  1089.9   107.1 1084.19
   116.9 1077.78   126.6  1072.3   131.3 1070.97   136.3 1069.56   141.3 1069.96
   146.1 1070.34   155.8 1073.85   165.5 1078.16   174.9 1081.47   184.2 1084.09
   193.6 1086.12   202.9 1088.24   212.3 1090.94   240.4 1099.98   259.1 1106.32
   277.8 1113.38
#Mann= 3 , 0 , 0
       0      .1       0   131.3    .045       0   141.3     .06       0
Bank Sta=131.3,141.3
XS Rating Curve= 0 ,0
Exp/Cntr=0.3,0.1

Type RM Length L Ch R = 1 ,1753.7  ,386.8,381.4,375.9
XS GIS Cut Line= 3
     1730161.759      166637.886     1730246.484      166530.863
      1730331.21      166423.841
#Sta/Elev= 30
     9.8 1114.51    19.5 1109.76    29.3  1105.2      39 1101.04    48.8 1097.52
    58.5  1093.9    68.2 1089.42      78 1083.65    87.8 1077.32    97.5 1070.78
   107.2 1064.09     117  1056.4   126.7 1049.82   136.5 1046.18   141.2 1046.12
   146.3 1046.05   151.2 1046.76     156 1047.46   165.8 1049.15   175.5 1050.71
   185.3 1052.14     195 1053.63   204.7 1056.05   214.5  1059.7   224.3 1063.56
     234 1067.09   243.8 1070.36   253.5  1073.6   263.2 1076.81     273 1079.92
#Mann= 3 , 0 , 0
       0     .06       0   141.2    .045       0   151.2     .06       0
Bank Sta=141.2,151.2
XS Rating Curve= 0 ,0
Exp/Cntr=0.3,0.1

Type RM Length L Ch R = 1 ,1372.3  ,404.4,406.5,408.6
XS GIS Cut Line= 3
     1730545.862      166709.522     1730610.629      166557.692
     1730668.416      166454.868
#Sta/Elev= 23
     9.7  1048.8    19.4 1045.64    48.5 1036.77    58.3 1034.41      68 1032.91
    97.1 1030.14   106.8 1029.16   126.2 1026.95   130.9 1026.57   135.9 1026.17
   140.9 1026.74   145.6 1027.27   155.4 1032.68   165.1 1041.09   174.9 1050.12
   184.7 1058.47   204.4 1074.75   214.2 1082.67     224 1089.81   233.9 1095.06
   263.4 1106.52   273.2 1110.58     283 1114.82
#Mann= 3 , 0 , 0
       0     .06       0   130.9    .045       0   140.9      .1       0
Bank Sta=130.9,140.9
XS Rating Curve= 0 ,0
Exp/Cntr=0.3,0.1

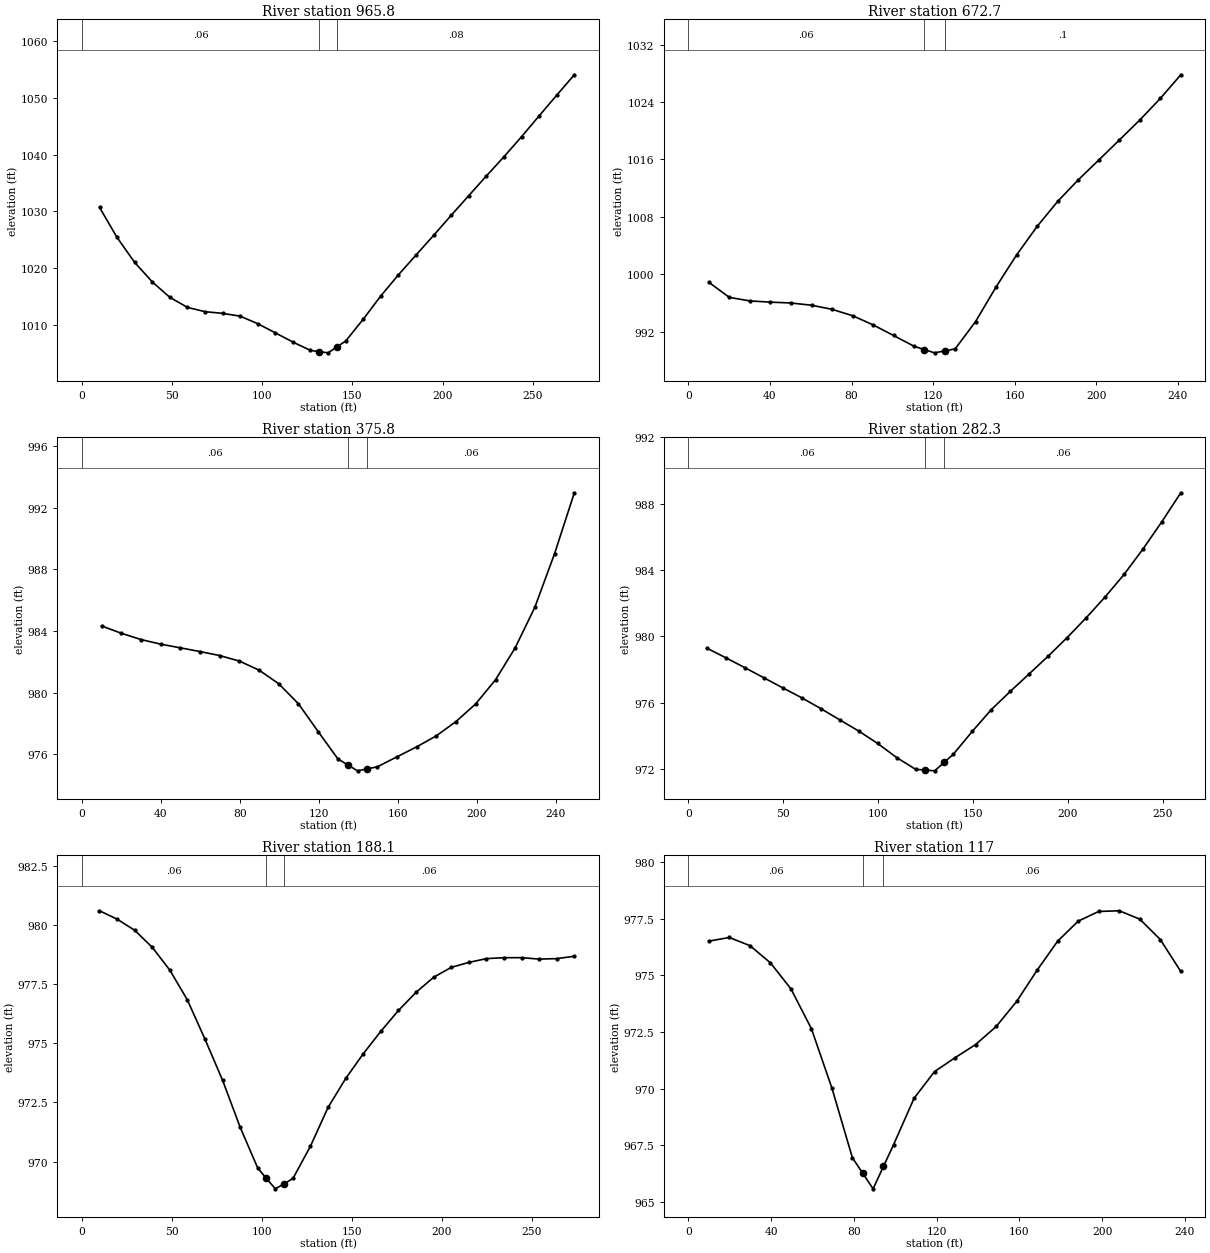
Type RM Length L Ch R = 1 ,965.8   ,296.7,293.1,289.6
XS GIS Cut Line= 3
     1730859.526      166925.882     1730925.601      166806.441
     1730991.676      166686.999
#Sta/Elev= 30
     9.8 1030.71    19.5 1025.44    29.2 1021.08      39 1017.64    48.7 1014.93
    58.5 1013.15    68.3 1012.39      78  1012.1    87.7 1011.61    97.5 1010.28
   107.3 1008.67     117 1007.05   126.7 1005.59   131.5 1005.38   136.5 1005.16
   141.5 1006.22   146.3 1007.25     156 1011.08   165.7 1015.15   175.5 1018.87
   185.2 1022.33     195  1025.8   204.7 1029.31   214.5 1032.79   224.2 1036.22
     234 1039.62   243.8 1043.16   253.5  1046.8   263.2 1050.42     273 1054.02
#Mann= 3 , 0 , 0
       0     .06       0   131.5    .045       0   141.5     .08       0
Bank Sta=131.5,141.5
XS Rating Curve= 0 ,0
Exp/Cntr=0.3,0.1

Type RM Length L Ch R = 1 ,672.7   ,287.2,296.9,306.7
XS GIS Cut Line= 2
      1731139.38      167060.961     1731217.949      166832.685
#Sta/Elev= 26
    10.1  998.86    20.1  996.76    30.2  996.27    40.2   996.1    50.3  995.98
    60.4  995.67    70.4   995.1    80.5  994.21    90.5  992.94   100.6  991.45
   110.7  989.94   115.7  989.48   120.7  989.03   125.7   989.3   130.8  989.58
   140.8  993.39   150.9  998.24   160.9 1002.67     171 1006.67   181.1 1010.16
   191.1 1013.14   201.2 1015.91   211.2 1018.68   221.3 1021.49   231.4 1024.51
   241.4  1027.8
#Mann= 3 , 0 , 0
       0     .06       0   115.7    .045       0   125.7      .1       0
Bank Sta=115.7,125.7
XS Rating Curve= 0 ,0
Exp/Cntr=0.3,0.1

Type RM Length L Ch R = 1 ,375.8   ,94.9,93.5,92.1
XS GIS Cut Line= 2
      1731333.68      167175.629     1731515.239      167004.688
#Sta/Elev= 27
      10  984.33    19.9  983.86    29.9  983.45    39.9  983.15    49.9  982.91
    59.8  982.67    69.8  982.41    79.8  982.05    89.8  981.46    99.7  980.58
   109.7  979.28   119.7  977.47   129.7   975.7   134.6  975.32   139.6  974.93
   144.6  975.06   149.6  975.19   159.6  975.84   169.6  976.49   179.5   977.2
   189.5  978.13   199.5  979.28   209.5  980.84   219.4   982.9   229.4  985.54
   239.4  989.02   249.4  992.97
#Mann= 3 , 0 , 0
       0     .06       0   134.6    .045       0   144.6     .06       0
Bank Sta=134.6,144.6
XS Rating Curve= 0 ,0
Exp/Cntr=0.3,0.1

Type RM Length L Ch R = 1 ,282.3   ,92.4,94.2,96
XS GIS Cut Line= 2
     1731395.911      167236.956     1731584.065      167058.209
#Sta/Elev= 28
      10  979.27      20  978.69    29.9   978.1    39.9  977.49    49.9  976.88
    59.9  976.28    69.9  975.63    79.9  974.95    89.8  974.28    99.8  973.53
   109.8  972.68   119.8  971.97   124.8  971.93   129.8  971.88   134.8  972.39
   139.7  972.89   149.7  974.27   159.7  975.58   169.7  976.68   179.7  977.74
   189.7  978.81   199.6  979.92   209.6  981.11   219.6  982.37   229.6  983.73
   239.6  985.27   249.5  986.91   259.5  988.66
#Mann= 3 , 0 , 0
       0     .06       0   124.8    .045       0   134.8     .06       0
Bank Sta=124.8,134.8
XS Rating Curve= 0 ,0
Exp/Cntr=0.3,0.1

Type RM Length L Ch R = 1 ,188.1   ,71.9,71.1,70.3
XS GIS Cut Line= 2
     1731448.349      167310.472     1731651.143      167126.789
#Sta/Elev= 30
     9.8  980.59    19.5  980.24    29.3  979.77    39.1  979.05    48.9  978.08
    58.6  976.83    68.4  975.17    78.2  973.43    87.9  971.46    97.7  969.73
   102.5  969.29   107.5  968.85   112.5  969.07   117.3  969.29     127  970.65
   136.8  972.29   146.6  973.51   156.4  974.56   166.1   975.5   175.9  976.38
   185.7  977.15   195.4  977.78   205.2   978.2     215  978.41   224.8  978.57
   234.5  978.61   244.3  978.61   254.1  978.55   263.8  978.57   273.6  978.67
#Mann= 3 , 0 , 0
       0     .06       0   102.5    .045       0   112.5     .06       0
Bank Sta=102.5,112.5
XS Rating Curve= 0 ,0
Exp/Cntr=0.3,0.1

Type RM Length L Ch R = 1 ,117     ,112.7,117,121.3
XS GIS Cut Line= 2
     1731507.807      167357.189     1731677.687      167190.494
#Sta/Elev= 26
     9.9  976.51    19.8  976.67    29.8  976.31    39.7  975.55    49.6   974.4
    59.5  972.64    69.4  970.02    79.3  966.94    84.3  966.26    89.3  965.57
    94.3  966.56    99.2  967.52   109.1  969.57     119  970.75   128.9  971.36
   138.8  971.94   148.8  972.74   158.7  973.85   168.6  975.23   178.5  976.51
   188.4  977.39   198.3  977.82   208.3  977.85   218.2  977.48   228.1  976.58
     238  975.17
#Mann= 3 , 0 , 0
       0     .06       0    84.3    .045       0    94.3     .06       0
Bank Sta=84.3,94.3
XS Rating Curve= 0 ,0
Exp/Cntr=0.3,0.1

Chan Stop Cuts=-1
Use User Specified Reach Order=0